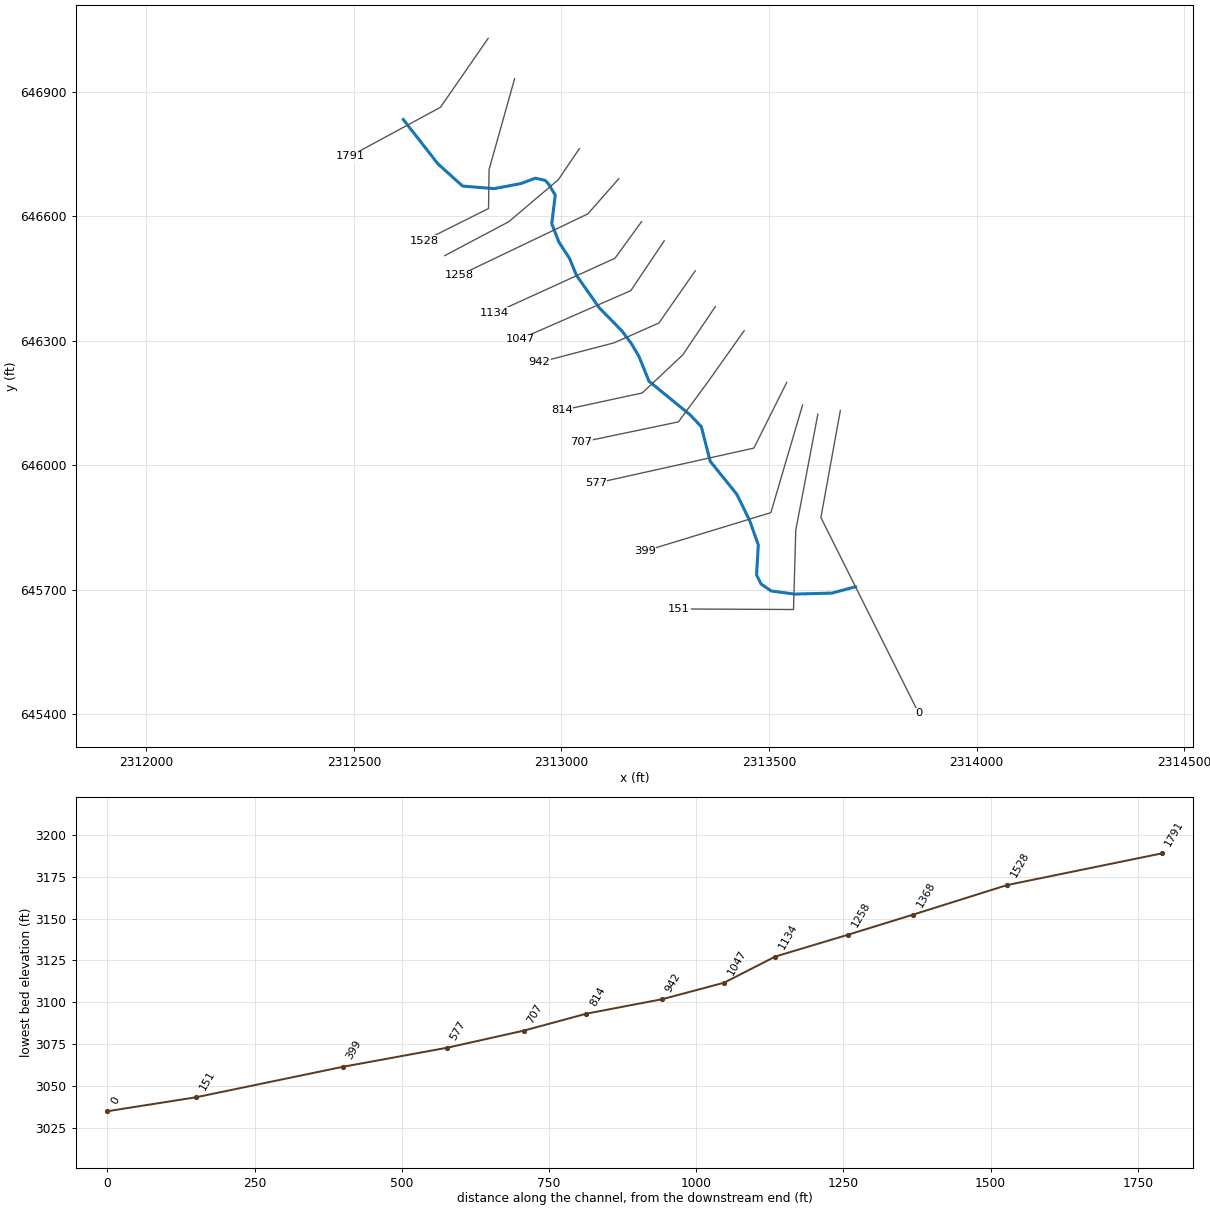
--- REDRN_1US.prj (project) ---

Proj Title=REDRN_1US
Current Plan=p01
Default Exp/Contr=0,0
English Units
Geom File=g01
Flow File=f01
Plan File=p01
BEGIN DESCRIPTION:
----------MODEL BY WOOD PLC 2022----------
AFH study
Randolph County, WV
HEC-RAS Version: RAS 6.2
Vertical Datum: NAVD88
Projection: NAD 1983 StatePlane West Virginia S FIPS 4702 (US Feet)
Terrain: 1-meter LIDAR (FEMA Region III 3DEP collected 2016-2018)
Land Use: 2019 NLCD
Hydrologic Method:
WV SIR2010-5033 regression equations
Additional Model Notes:
KWSE at DS boundary with REDRN_1DS and ROSERN
END DESCRIPTION:
DSS Export Rating Curves= 0
DSS Export Rating Curve Sorted= 0
DSS Export Volume Flow Curves= 0
DXF OffsetX= 0
DXF OffsetY= 0
DXF ScaleX= 0
DXF ScaleY= 0

--- REDRN_1US.p01 (plan) ---

Plan Title=Floodplain
Program Version=6.20
Short Identifier=Floodplain
Geom File=g01
Flow File=f01
Subcritical Flow
K Sum by GR= 0
Std Step Tol= 0.01
Critical Tol= 0.01
Num of Std Step Trials= 20
Max Error Tol= 0.3
Flow Tol Ratio= 0.001
Split Flow NTrial= 30
Split Flow Tol= 0.02
Split Flow Ratio= 0.02
Log Output Level= 0
Friction Slope Method= 1
Unsteady Friction Slope Method= 2
Unsteady Bridges Friction Slope Method= 1
Parabolic Critical Depth
Global Vel Dist= 0 , 0 , 0
Global Log Level= 0
CheckData=True
Encroach Param=-1 ,0,0, 0
Mapping Interval=1HOUR
Computation Time Step Use Courant=        0
Computation Time Step Use Time Series=    0
Computation Time Step Count To Double=0
Computation Time Step Max Doubling=0
Computation Time Step Max Halving=0
Computation Time Step Residence Courant=0
Run HTab= 0
Run UNet= 0
Run Sediment= 0
Run PostProcess= 0
Run WQNet= 0
Run RASMapper=-1
UNET Theta= 0
UNET Theta Warmup= 0
UNET ZTol= 0
UNET ZSATol= 0
UNET MxIter= 0
UNET Max Iter WO Improvement= 0
UNET MaxInSteps= 0
UNET DtIC= 0
UNET DtMin= 0
UNET MaxCRTS= 0
UNET WFStab= 0
UNET SFStab= 0
UNET WFX= 1
UNET SFX= 1
UNET Gravity=32.174
UNET 1D Methodology=Finite Difference
UNET DSS MLevel= 1
UNET Pardiso=0
UNET DZMax Abort= 0
UNET Use Existing IB Tables= 0
UNET Froude Reduction=False
UNET Froude Limit= 0
UNET Froude Power= 0
UNET D1 Cores= 0
UNET WindReference=Eulerian
UNET WindDragFormulation=Hsu (1988)
UNET D2 Coriolis=0
UNET D2 Cores= 0
UNET D2 Theta= 1
UNET D2 Theta Warmup= 1
UNET D2 Z Tol= 0.01
UNET D2 Volume Tol= 0.01
UNET D2 Max Iterations= 20
UNET D2 Equation= 0
UNET D2 RampUpFraction=0.1
UNET D2 TimeSlices= 1
UNET D2 Turbulence Formulation=Non-Conservative (original)
UNET D2 Eddy Viscosity=0.3
UNET D2 Transverse Eddy Viscosity=0.1
UNET D2 Smagorinsky Mixing=0
UNET D2 BCVolumeCheck=0
UNET D2 Cores=0
UNET D2 SolverType=PARDISO (Direct)
UNET D2 Minimum Iterations= 2147483647
UNET D2 Maximum Iterations= 2147483647
UNET D2 Restart Number= 10
UNET D2 Relaxation Coeff=1.3
UNET D2 SOR Precondition Iterations= 10
UNET D2 ILUT Maximum Fill= 8
UNET D2 ILUT Tolerance=1E-08
UNET D1D2 MaxIter= 0
UNET D1D2 ZTol=0.01
UNET D1D2 QTol=0.1
UNET D1D2 MinQTol=1
Write IC File= 0
Write IC File at Fixed DateTime=0
Write IC File at Sim End=0
Echo Input=False
Echo Parameters=False
Echo Output=False
Write Detailed= 0
HDF Write Warmup=0
HDF Write Time Slices=0
HDF Flush=0
HDF Compression= 1
HDF Chunk Size= 1
HDF Spatial Parts= 1
HDF Use Max Rows=0
HDF Fixed Rows= 1
Calibration Method= 0
Calibration Iterations= 20
Calibration Max Change=0.05
Calibration Tolerance=0.2
Calibration Maximum=1.5
Calibration Minimum=0.5
Calibration Optimization Method= 1
WQ AD Non Conservative
WQ ULTIMATE=-1
WQ Max Comp Step=1HOUR
WQ Output Interval=15MIN
WQ Output Selected Increments= 0
WQ Output face flow=0
WQ Output face velocity=0
WQ Output face area=0
WQ Output face dispersion=0
WQ Output cell volume=0
WQ Output cell surface area=0
WQ Output cell continuity=0
WQ Output cumulative cell continuity=0
WQ Output face conc=0
WQ Output face dconc_dx=0
WQ Output face courant=0
WQ Output face peclet=0
WQ Output face adv mass=0
WQ Output face disp mass=0
WQ Output cell mass=0
WQ Output cell source sink temp=0
WQ Output nsm pathways=0
WQ Output nsm derived pathways=0
WQ Create Restart=0
WQ Fixed Restart=0
WQ System Summary=0
WQ Write To DSS=0
Sorting and Armoring Iterations= 10
XS Update Threshold= 0.02
Bed Roughness Predictor= 0
Hydraulics Update Threshold= 0.02
Energy Slope Method= 1
Volume Change Method= 1
Sediment Retention Method= 0
Sediment TS Multiplier= 1
Warm Up Method= 0
XS Weighting Method= 0
Number of US Weighted Cross Sections= 1
Number of DS Weighted Cross Sections= 1
Upstream XS Weight=0
Main XS Weight=1
Downstream XS Weight=0
Number of DS XS's Weighted with US Boundary= 1
Upstream Boundary Weight= 1
Weight of XSs Associated with US Boundary= 0
Number of US XS's Weighted with DS Boundary= 1
Downstream Boundary Weight= 0.5
Weight of XSs Associated with DS Boundary= 0.5
Percentile Method= 0
Sediment Output Level= 3
Mass or Volume Output= 0
Output Increment Type= 1
Profile and TS Output Increment= 1
Transport Output Increment 1
XS Output Flag= 0
XS Output Increment= 10
Read HDF5 Sediment Hotstart= 0
Sediment Hotstart Type= 0
Write Gradation File= 0
Read Gradation Hotstart= 0
Write HDF5 File= 1
Write Binary Output= 1
Write DSS Sediment File= 0
DSS Sediment Output Type= 1
SV Curve= 0
Specific Gage Flag= 0
Subcell Erosion Methods= 0
Subcell Deposition Methods= 0
Advection Scheme= 1
Matrix Solver= 0
Implicit Weighting Factor= 1
Maximum Outer Loop Convergence Iterations= 5
Convergence Maximum Absolute= 0.001
Convergence RMSE= 0.0001
Grain Fractions Max Abs Error= 0.001
Max Subgrid Regions= 1
Max Subgrid Length Scale= 3.402823E+38
Initial Layer Thickness= 3.402823E+38
Min Layer Thickness= 3.402823E+38
Max Layer Thickness= 3.402823E+38
Number of Layers= 5

--- REDRN_1US.f01 (steady flow) ---

Flow Title=Flow
Program Version=6.20
Number of Profiles= 1
Profile Names=P100yr
River Rch & RM=REDRN_1US,Main            ,1791
     320
River Rch & RM=REDRN_1US,Main            ,0
     715
Boundary for River Rch & Prof#=REDRN_1US,Main            , 1
Up Type= 0
Dn Type= 1
Dn Known WS=3038.4
DSS Import GetInterval= 0
DSS Import GetPeak= 0
DSS Import FillOption= 0

--- REDRN_1US.g01 (geometry) ---

Geom Title=Geometry
Program Version=6.20

River Reach=REDRN_1US       ,Main
Reach XY= 30
   2312619.11654646832.5030294692312702.26900002646726.047000006
2312761.77542825646672.3453501452312837.99553514646666.149389184
2312901.87800002 646678.34800002     2312937.295646691.369000018
2312960.47200002646686.1600000112312968.54500003646677.827000007
2312984.95100002646650.7440000032312976.62241205646581.533180092
2312993.82164803646537.378274693     2313019.066646498.659999996
2313036.21701381646457.0383245942313091.21737191646378.977495906
2313145.62800005646323.4000000212313168.02400005646293.452000022
2313186.77400003646261.6810000092313210.86983065646202.224553743
2313309.90278709646121.1804884422313336.77400003646092.931000009
2313358.12800002 646009.59800002     2313422.191645930.171000004
2313453.12461567645866.9923078422313474.01400001645808.296000019
2313469.84700003645735.6400000012313480.52399999645714.025000006
     2313505.264 645697.098000022313561.77400002645689.633000001
     2313651.705645692.0629999942313708.15725239 645707.27085115

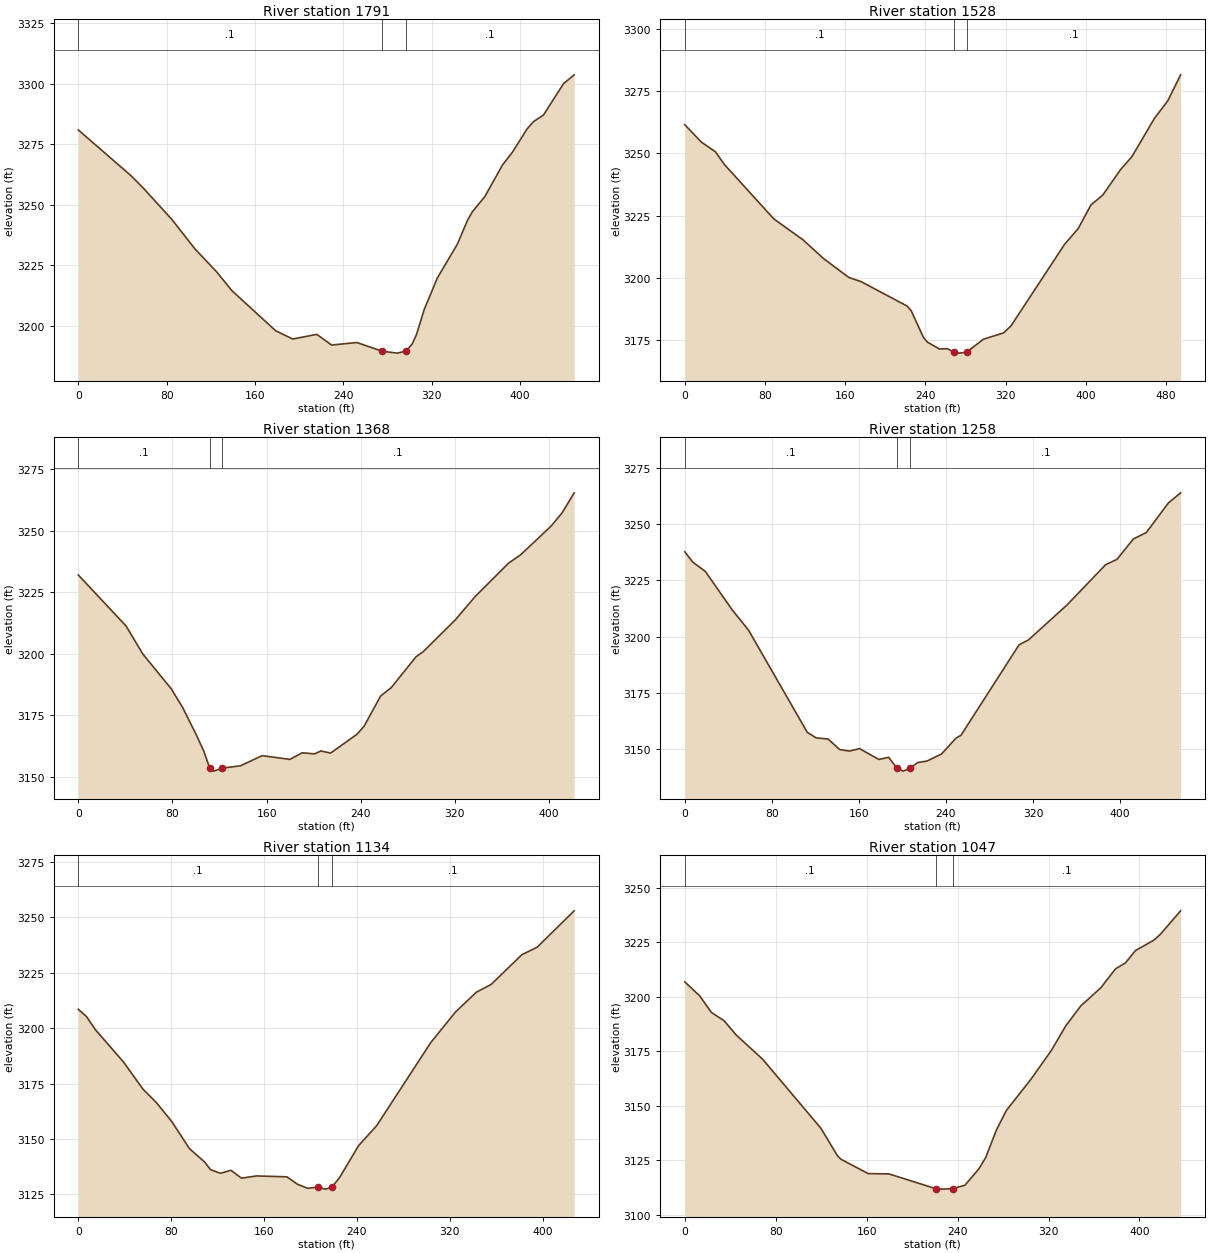
Type RM Length L Ch R = 1 ,1791    ,253.1,262.6,269.7
XS GIS Cut Line= 3
2312823.38389645647028.2089200092312708.47568089646862.093590223
2312491.05733876646744.546273351
#Sta/Elev= 30
       0 3280.97    47.6 3262.12    59.1 3256.84      85 3243.85   105.8 3231.74
   125.3 3222.35   139.2 3214.53   178.8 3198.01   194.2 3194.61     216 3196.53
   229.4 3192.13   252.3 3193.16   275.1 3189.58   288.7 3188.78  296.74 3189.59
   302.4 3192.57   306.2 3196.32   313.2 3206.69   325.1 3219.76   343.3 3233.77
   352.4 3243.57   356.9 3247.18   368.2 3253.44   384.2  3266.5   393.3 3271.85
   406.5 3281.42   412.4 3284.45   421.3 3287.14   439.4 3300.05   449.1 3303.74
#Mann= 3 ,0,0
       0      .1       0   275.1    .045       0  296.74      .1       0
Bank Sta=275.1,296.74
XS Rating Curve= 0 ,0
Exp/Cntr=0.3,0.1

Type RM Length L Ch R = 1 ,1528    ,162.2,159.6,153.3
XS GIS Cut Line= 4
2312886.99194842646930.6752331472312825.60625238646712.414980557
 2312824.2421258646618.2902466282312668.73169583646540.535031642
#Sta/Elev= 30
       0 3261.52    16.5 3254.56    30.6 3250.66    39.2 3245.71    88.8 3223.75
   117.9 3215.37   138.7 3207.75   163.6 3200.29   176.1 3198.55   221.8  3188.8
   225.9 3186.92     238 3176.31     242 3174.34     254 3171.58     262 3171.71
  268.433170.309     274 3169.92   281.3 3170.33     298 3175.51     318 3178.02
   325.4 3180.81   379.1 3213.65   392.5 3219.86   405.2 3229.33   417.1 3233.33
   434.8 3243.53   446.2 3248.77   468.5 3264.02   481.9  3271.1   494.7 3281.52
#Mann= 3 ,-1,0
       0      .1       0  268.43    .045       0   281.3      .1       0
Bank Sta=268.43,281.3
XS Rating Curve= 0 ,0
Exp/Cntr(USF)=0,0
Exp/Cntr=0.3,0.1

Type RM Length L Ch R = 1 ,1368    ,109.9,110.3,107.9
XS GIS Cut Line= 4
2313043.11516073646762.5670358322312992.22347465646687.534421745
2312872.82374963646586.4035071062312718.84377637646504.846317881
#Sta/Elev= 30
       0 3232.05    40.6  3211.3    54.8 3199.95      79 3185.76    88.7 3178.16
   100.5 3166.81   106.5 3160.59   111.7 3153.54   115.1 3152.31   122.2 3153.53
   137.8 3154.47   156.2 3158.61   179.8 3157.08   190.3 3159.77   200.8 3159.32
   206.1 3160.51   214.4 3159.66   236.7 3167.25   242.8 3170.51   256.9 3182.84
     266 3186.28     287 3198.81   293.1 3200.87   320.3 3213.76   337.3 3223.31
   365.6 3236.85   375.8 3240.22   401.8 3251.93   411.3 3257.42   421.4 3265.46
#Mann= 3 ,-1,0
       0      .1       0   111.7    .045       0   122.2      .1       0
Bank Sta=111.7,122.2
XS Rating Curve= 0 ,0
Exp/Cntr(USF)=0,0
Exp/Cntr=0.3,0.1

Type RM Length L Ch R = 1 ,1258    ,123.6,123.7,123.3
XS GIS Cut Line= 3
2313137.87059971646689.9961625242313063.49609539646605.423706001
2312754.02264894646457.323763531
#Sta/Elev= 30
       0 3237.73     7.4 3233.09    18.8 3229.06    43.7 3211.86    58.5 3203.01
   112.6 3157.57   120.7 3155.13   131.7 3154.61   142.3 3149.96   151.3 3149.26
   160.6 3150.36   178.4 3145.54   187.3  3146.5  194.913141.734   200.6 3140.36
  207.223141.676   213.9 3144.16   222.7 3144.85     236 3147.99   249.3 3155.03
   253.8 3156.24   307.2 3196.42   315.9 3198.63   351.3 3214.13   386.8 3232.01
   397.2 3234.36   412.2  3243.4   424.2 3246.27   444.5 3259.43   455.7  3263.9
#Mann= 3 ,0,0
       0      .1       0  194.91    .045       0  207.22      .1       0
Bank Sta=194.91,207.22
XS Rating Curve= 0 ,0
Exp/Cntr(USF)=0,0
Exp/Cntr=0.3,0.1

Type RM Length L Ch R = 1 ,1134    ,88.9,87,88
XS GIS Cut Line= 3
2313192.76210832646586.5876107662313128.82127197646498.505846403
2312839.13013584646366.709428616
#Sta/Elev= 30
       0 3208.49     7.2 3205.11    14.6 3199.35    38.7 3184.84    55.8 3172.39
    67.3 3166.36    80.8 3157.62    95.7 3145.62   108.8 3139.58   113.9 3136.09
   122.4 3134.49   131.5 3135.82   140.5 3132.29   153.5 3133.28   179.7 3132.88
   188.7 3129.55   197.4 3127.73   206.2 3128.19     213 3127.33   218.3 3128.12
   225.1 3132.59   241.4 3146.95   256.9  3155.9   303.6 3193.49   324.9 3207.28
   342.9 3216.22   355.6 3219.72     382 3233.11   395.2 3236.51   427.1 3252.93
#Mann= 3 ,-1,0
       0      .1       0   206.2    .045       0   218.3      .1       0
Bank Sta=206.2,218.3
XS Rating Curve= 0 ,0
Exp/Cntr(USF)=0,0
Exp/Cntr=0.3,0.1

Type RM Length L Ch R = 1 ,1047    ,103.2,104.9,103.8
XS GIS Cut Line= 3
2313247.47568331646540.6037450372313166.99221516646420.560606112
2312899.74635065646303.720543205
#Sta/Elev= 30
       0 3206.78    13.1  3200.4    23.4 3192.79    34.7 3188.92    45.2 3182.42
    68.3 3171.43   119.7 3139.69   134.2 3127.11   137.5  3125.4   161.4 3118.85
   179.6 3118.72  220.673111.958   226.2 3111.74  235.513111.958   246.4 3113.52
   258.6 3120.98   264.7 3126.19   274.2 3138.94   282.9 3147.81   304.8 3162.34
   322.4 3175.29   335.3 3186.73   348.4 3195.79   365.9 3204.04     379  3212.8
   387.7 3215.51   396.4 3221.14   412.6 3225.91   418.3 3228.58   436.2 3239.38
#Mann= 3 ,0,0
       0      .1       0  220.67    .045       0  235.51      .1       0
Bank Sta=220.67,235.51
XS Rating Curve= 0 ,0
Exp/Cntr(USF)=0,0
Exp/Cntr=0.3,0.1

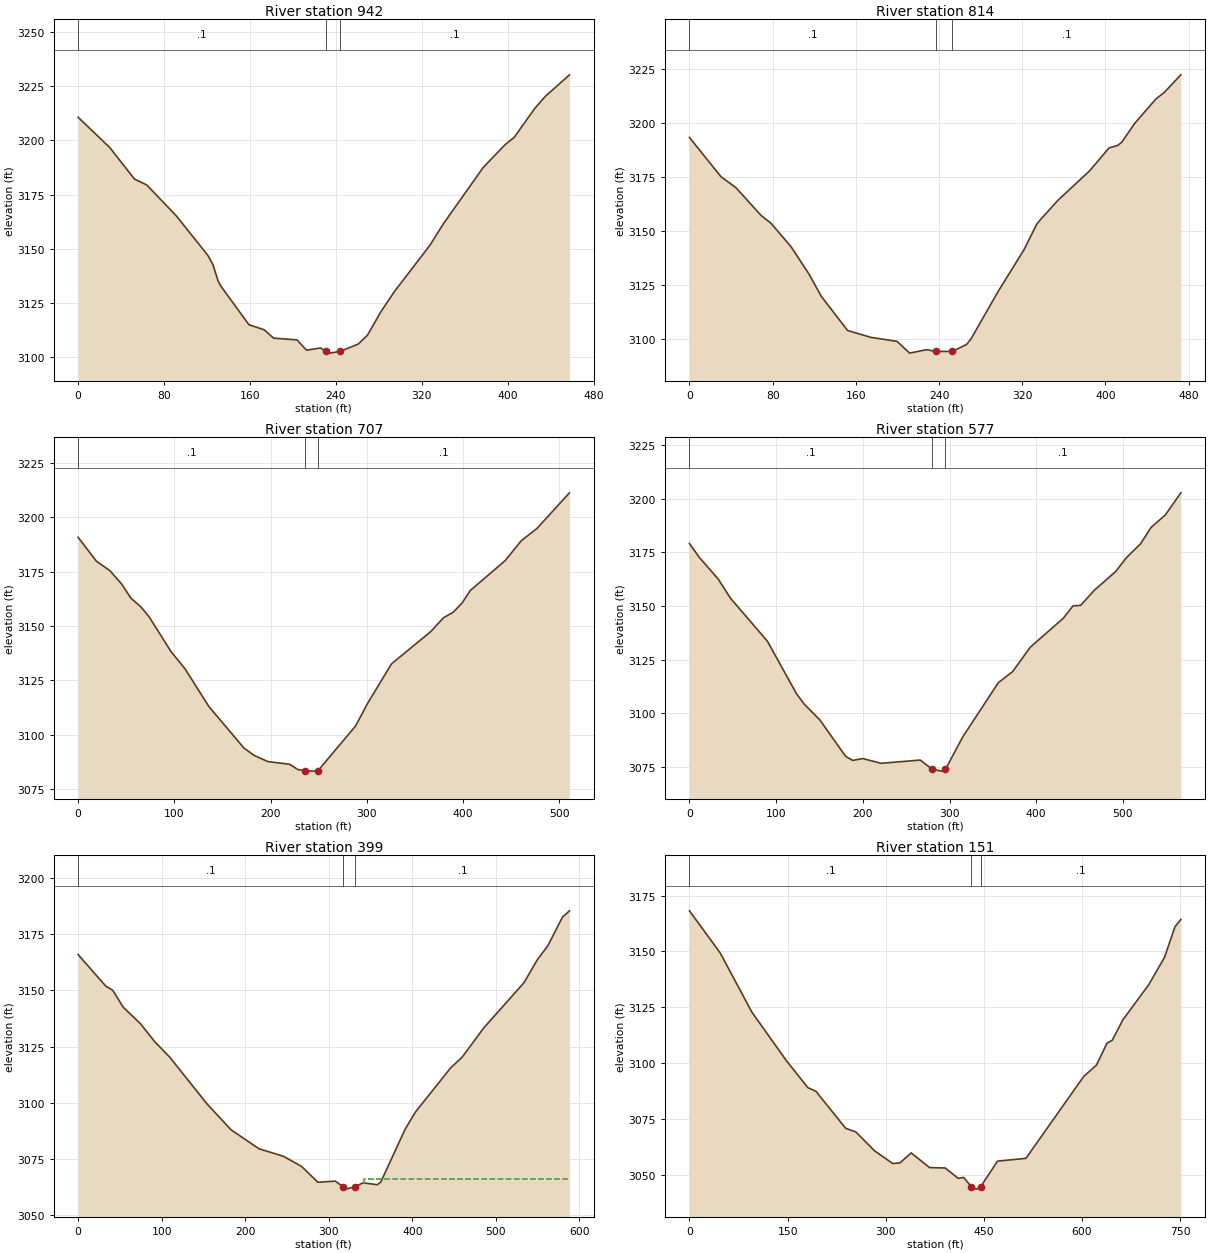
Type RM Length L Ch R = 1 ,942     ,126.5,128.7,131.8
XS GIS Cut Line= 4
2313322.14832702646468.2363229722313234.84422598646342.736677733
2313127.07822627646294.9922474792312946.30637062646247.604216983
#Sta/Elev= 30
       0  3210.6    29.5 3196.65    52.5 3182.15      64 3179.39    91.4 3165.22
   120.7 3147.08   125.5 3142.82   130.4 3135.19   132.9 3132.86   159.1 3115.04
   173.3 3112.71     182 3108.88   203.9 3108.05   212.7 3103.32   225.8 3104.34
  230.693102.801   234.5 3101.96     244 3102.79   260.8  3106.1   269.5 3110.23
     282 3121.06   294.4 3130.22   327.5 3151.55   340.1 3161.49   377.1 3187.38
   397.8 3198.06   406.1 3201.33   425.3 3214.68     435 3220.19   457.6 3230.15
#Mann= 3 ,-1,0
       0      .1       0  230.69    .045       0     244      .1       0
Bank Sta=230.69,244
XS Rating Curve= 0 ,0
Exp/Cntr(USF)=0,0
Exp/Cntr=0.3,0.1

Type RM Length L Ch R = 1 ,814     ,105.1,106.2,107.8
XS GIS Cut Line= 4
2313370.64883266646382.1843052872313291.70147349646265.394410316
2313194.48530393646174.0503583852313000.70542233646132.293077501
#Sta/Elev= 30
       0 3193.29    30.2 3175.16    44.7 3170.03    68.8 3157.18    78.5 3153.49
    97.6 3142.72   114.9 3130.01   126.7 3119.72   152.1 3103.82   174.7 3100.61
   199.7 3098.78   211.7 3093.33   228.1 3094.93  237.153094.116  252.913094.124
   266.6 3097.36     271 3100.11   297.2 3122.19   321.7 3141.21     334 3153.06
   337.6 3155.24   354.5 3164.22   384.8 3177.81   403.6 3188.47   411.8 3189.57
   415.9 3191.16   428.1 3199.76   448.7 3211.18   456.8 3214.22   472.6 3222.33
#Mann= 3 ,-1,0
       0      .1       0  237.15    .045       0  252.91      .1       0
Bank Sta=237.15,252.91
XS Rating Curve= 0 ,0
Exp/Cntr(USF)=0,0
Exp/Cntr=0.3,0.1

Type RM Length L Ch R = 1 ,707     ,134.3,130.3,123.9
XS GIS Cut Line= 4
2313439.96990233646324.0522560362313354.02992787646202.644990533
 2313281.7312192646104.4278768682313047.10144767646055.319320035
#Sta/Elev= 30
       0 3190.85    19.1 3179.82    32.9 3175.54      45 3169.46      55 3162.76
      65 3158.93    73.7 3154.29    96.6 3138.19     111 3130.37   135.8    3113
   172.1 3093.93   182.6 3090.53   196.9 3087.66   219.8 3086.39   228.4 3083.94
  235.363083.489   244.9 3083.24  249.253083.472   288.3 3104.07   300.9 3114.56
   325.6 3132.64   366.3 3147.44   379.5 3153.81   389.7  3156.4     399 3160.69
   407.2  3166.3   443.7 3180.16   460.3 3189.26   476.6 3194.91   510.4 3211.31
#Mann= 3 ,-1,0
       0      .1       0  235.36    .045       0  249.25      .1       0
Bank Sta=235.36,249.25
XS Rating Curve= 0 ,0
Exp/Cntr(USF)=0,0
Exp/Cntr=0.3,0.1

Type RM Length L Ch R = 1 ,577     ,176.7,177.7,178.2
XS GIS Cut Line= 3
2313542.45476948 646199.503386972313463.33542791646041.264703843
2313082.74411246645956.688855964
#Sta/Elev= 30
       0 3179.06    11.5 3172.52    33.2 3162.49    47.3 3153.59    89.9 3133.55
   123.3 3109.21   132.3 3104.26   150.2 3096.99   180.2 3079.91   188.3 3078.03
   199.8 3078.89   221.1 3076.68   266.2  3078.2  279.773073.966   290.3 3073.04
  295.293073.872   315.4  3089.1   356.3 3114.25   372.7 3119.36   393.2  3130.8
   431.1  3144.2   442.4 3149.99   451.2 3150.26     467 3157.28   491.6 3166.01
   503.9  3172.4   520.3 3178.93   532.5 3186.56   548.9 3192.37   566.8 3202.67
#Mann= 3 ,-1,0
       0      .1       0  279.77    .045       0  295.29      .1       0
Bank Sta=279.77,295.29
XS Rating Curve= 0 ,0
Exp/Cntr(USF)=0,0
Exp/Cntr=0.3,0.1

Type RM Length L Ch R = 1 ,399     ,238.6,248.6,256.5
XS GIS Cut Line= 3
2313580.65031368646144.9383238232313504.25922527645885.754273873
2313200.05899823645792.993666522
#Sta/Elev= 30
       0 3165.84    33.1 3151.85    41.5 3149.96      54 3142.48    74.8 3135.07
    91.5 3127.24   109.7 3120.27     154 3099.65   183.2 3087.96   216.6 3079.56
   245.8 3076.23   267.5 3071.74     287 3064.69   307.9 3065.19  317.093062.739
   320.5 3061.64   331.6 3062.73   341.2 3064.45   358.1  3063.6   362.3 3064.76
   391.6 3088.36   404.1 3096.04   445.9 3115.47   459.8 3120.31   485.4 3133.18
   533.8 3153.38   549.5 3163.42   562.4 3169.84   579.8 3182.49   588.2 3185.28
#Mann= 3 ,-1,0
       0      .1       0  317.09    .045       0   331.6      .1       0
#XS Ineff= 2 , 0
                          342.11         3066.17
Permanent Ineff=
       F       F
Bank Sta=317.09,331.6
XS Rating Curve= 0 ,0
Exp/Cntr(USF)=0,0
Exp/Cntr=0.3,0.1

Type RM Length L Ch R = 1 ,151     ,144.9,150.8,155.7
XS GIS Cut Line= 4
 2313617.4817313646123.1122985642313564.28079474645843.466349933
2313558.82428842645652.4886289172313283.27071953645653.852755496
#Sta/Elev= 30
       0 3168.19    46.8 3149.41    95.6 3122.73   148.6 3100.92   181.1 3088.97
   193.3 3087.37   238.8 3070.78   254.4 3069.15   282.9 3060.72     311 3054.98
     322 3055.33     339 3059.77     367  3053.2     391 3053.01     411 3048.36
   419.3 3048.78   430.9 3044.62   438.7 3043.54  445.123044.583     471 3056.09
   514.4 3057.32   602.4 3093.86   622.4 3099.16   638.4 3108.92   646.4  3110.2
   662.6 3119.34   702.4 3135.18   726.4 3147.38   742.4 3161.11   751.3 3164.32
#Mann= 3 ,-1,0
       0      .1       0   430.9    .045       0  445.12      .1       0
Bank Sta=430.9,445.12
XS Rating Curve= 0 ,0
Exp/Cntr(USF)=0,0
Exp/Cntr=0.3,0.1

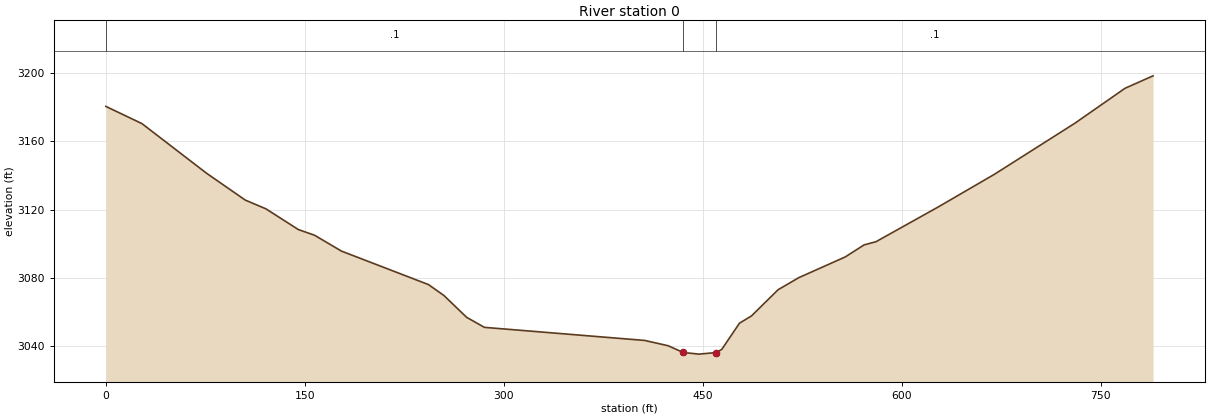
Type RM Length L Ch R = 1 ,0       ,271.4,269.3,266.6
XS GIS Cut Line= 3
2313671.68253824646131.9018663142313624.79165998645874.002035879
2313860.62519476645402.334966313
#Sta/Elev= 30
       0 3180.51    27.2 3170.41    75.9 3141.31   105.1 3125.56   120.7 3120.42
   145.1 3108.28   157.3 3104.96   177.6 3095.65   243.2 3076.01   254.8 3069.64
     272  3056.8   285.4 3050.92   406.2 3043.25     424 3040.12   435.2  3036.2
   447.1 3035.22   459.8 3036.12   464.3 3037.95   477.7 3053.38   486.7 3057.61
   506.8 3072.98   522.4 3080.07   557.4 3092.21   571.6 3099.27   580.6 3101.15
   627.5 3121.52     670 3140.74   730.4 3170.56   768.4 3191.15   789.5 3198.45
#Mann= 3 ,-1,0
       0      .1       0   435.2    .045       0   459.8      .1       0
Bank Sta=435.2,459.8
XS Rating Curve= 0 ,0
Exp/Cntr=0.3,0.1
LCMann Table=0

Chan Stop Cuts=-1
Use User Specified Reach Order=0
Composite Channel Slope=5